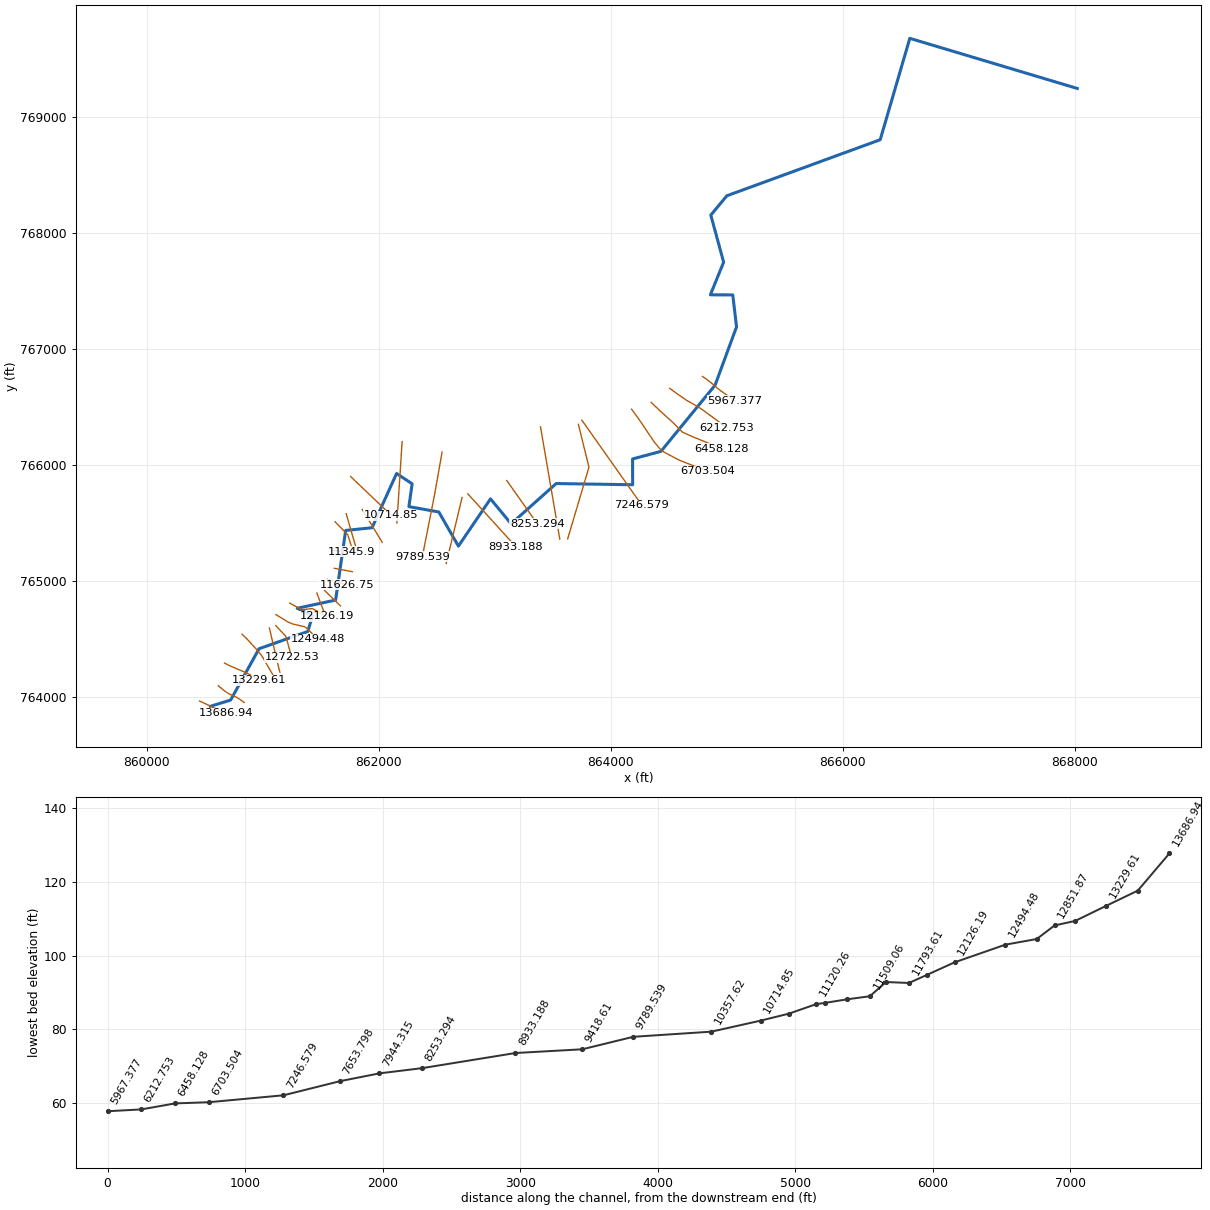
--- 9801_ras.prj (project) ---

Proj Title=9801
Current Plan=p01
Default Exp/Contr=0.3,0.1
English Units
Geom File=g01
Flow File=f01
Plan File=p01
Y Axis Title=Elevation
X Axis Title(PF)=Main Channel Distance
X Axis Title(XS)=Station
BEGIN DESCRIPTION:
RFD model 9801 exported to HEC-RAS
END DESCRIPTION:

--- 9801_ras.p01 (plan) ---

Plan Title=Plan 01
Program Version=4.10
Short Identifier=Plan 01
Geom File=g01
Flow File=f01
Subcritical Flow
Calc Critical at every XS
Secant Critical Depth

--- 9801_ras.f01 (steady flow) ---

Flow Title=Flow 01
Program Version=5.01
Number of Profiles= 6
Profile Names=10yr,25yr,50yr,100yr,100plus,500yr
River Rch & RM=9801,34,13686.94
  194.96  298.67  391.96  472.26   689.5 1123.11
River Rch & RM=9801,34, 13457.1
  675.63 1043.76 1378.79 1668.06 2435.36 3344.79
River Rch & RM=9801,34,13229.61
  858.81 1326.96 1753.44 2121.11 3096.82 4109.31
River Rch & RM=9801,34,13002.12
  864.21 1335.41 1764.71 2134.83 3116.85 4132.49
River Rch & RM=9801,34,12851.87
  870.28 1344.91 1777.37 2150.25 3139.36 4158.51
River Rch & RM=9801,34,12722.53
  873.65 1350.18 1784.39  2158.8 3151.85 4172.94
River Rch & RM=9801,34,12494.48
  876.67 1354.91 1790.71 2166.49 3163.08 4185.91
River Rch & RM=9801,34,12126.19
   879.7 1359.65 1797.02 2174.18 3174.31 4198.86
River Rch & RM=9801,34,11923.83
  882.72 1364.38 1803.33 2181.86 3185.52  4211.8
River Rch & RM=9801,34,11793.61
  884.75 1367.54 1807.55    2187 3193.01 4220.41
River Rch & RM=9801,34,11626.75
  885.76 1369.13 1809.66 2189.56 3196.76 4224.72
River Rch & RM=9801,34,11509.06
  886.78 1370.71 1811.77 2192.13 3200.51 4229.02
River Rch & RM=9801,34, 11345.9
  889.09 1374.34 1816.62 2198.05 3209.16 4239.06
River Rch & RM=9801,34,11182.21
  961.78  1488.3 1968.76 2383.52 3479.93  4549.9
River Rch & RM=9801,34,10921.74
  976.58  1511.6 1999.97 2421.66 3535.63 4613.84
River Rch & RM=9801,34,10714.85
  979.45 1516.14 2006.04 2429.09 3546.48  4626.3
River Rch & RM=9801,34,10357.62
  982.32 1520.67 2012.12 2436.52 3557.32 4638.76
River Rch & RM=9801,34,9789.539
  993.79 1538.75 2036.36 2466.19 3600.64 4688.45
River Rch & RM=9801,34, 9418.61
 1002.19 1551.95 2054.01 2487.72 3632.06 4724.21
River Rch & RM=9801,34,8933.188
  1183.9 1835.77 2432.09 2947.59 4303.48 5472.06
River Rch & RM=9801,34,8253.294
  1193.7 1851.24 2452.84 2972.98 4340.55 5513.48
River Rch & RM=9801,34,7944.315
 1198.58 1858.95 2463.19 2985.65 4359.05 5534.15
River Rch & RM=9801,34,7653.798
 1295.75 2011.75 2667.66 3235.33 4723.58 5936.29
River Rch & RM=9801,34,7246.579
 1302.34 2022.17 2681.65 3252.45 4748.58 5963.89
River Rch & RM=9801,34,6703.504
 1561.53 2432.29  3232.7 3927.67 5734.39 7038.71
River Rch & RM=9801,34,6458.128
 1566.97 2440.89 3244.27 3941.85  5755.1    7061
River Rch & RM=9801,34,6212.753
 1581.78 2464.37 3275.84 3980.57 5811.63 7121.88
River Rch & RM=9801,34,5967.377
 1585.46 2470.21  3283.7 3990.22 5825.72 7137.07
River Rch & RM=9801,34,5722.002
 1597.47 2489.33  3309.5 4021.94 5872.04 7187.22
River Rch & RM=9801,34,5476.627
  1601.9  2496.4 3319.05  4033.7  5889.2 7205.84
River Rch & RM=9801,34, 5373.45
    1603 2498.16 3321.44 4036.64 5893.49 7210.49
River Rch & RM=9801,34,4899.201
 1607.16 2504.79 3330.38 4047.66 5909.58 7227.93
Boundary for River Rch & Prof#=9801,34,1
Up Type= 0
Dn Type= 2
Boundary for River Rch & Prof#=9801,34,2
Up Type= 0
Dn Type= 2
Boundary for River Rch & Prof#=9801,34,2
Up Type= 0
Dn Type= 2
Boundary for River Rch & Prof#=9801,34,2
Up Type= 0
Dn Type= 2
Boundary for River Rch & Prof#=9801,34,2
Up Type= 0
Dn Type= 2
Boundary for River Rch & Prof#=9801,34,2
Up Type= 0
Dn Type= 2

--- 9801_ras.g01 (geometry) ---

Geom Title=9801
Program Version=4.10

River Reach=9801,34
Reach XY= 30
860548.193035841763915.771240607860722.238174707763969.156657249
860967.463869184764411.864990607861387.168730319764560.302490607
861428.835396975764695.719157264861296.890952498764760.823323995
861627.620119184764831.569851726861713.991647005765431.830268338
861941.856230259765455.267768368 862153.22775808765923.149712831
862287.342341363765834.174018368862259.564563602765637.125407308
862517.316883147765591.202929437862686.478886694765296.664553702
862963.123591363765704.399712816863141.074980289765489.121935084
863529.529841363765836.344157264864188.818035811765825.927490652
 864188.38400808766048.149712831864433.175674766 766114.12193507
 864899.32150805766684.000407249865084.651369184767187.038601711
865052.099285871767463.080268368864858.956924707767463.514296144
864973.430657446767745.188155204 864862.82652846768151.150544971
865001.266655624768317.720552623866323.605961114768801.005224466
866578.666805893769675.270281821868023.091262072769243.054627478

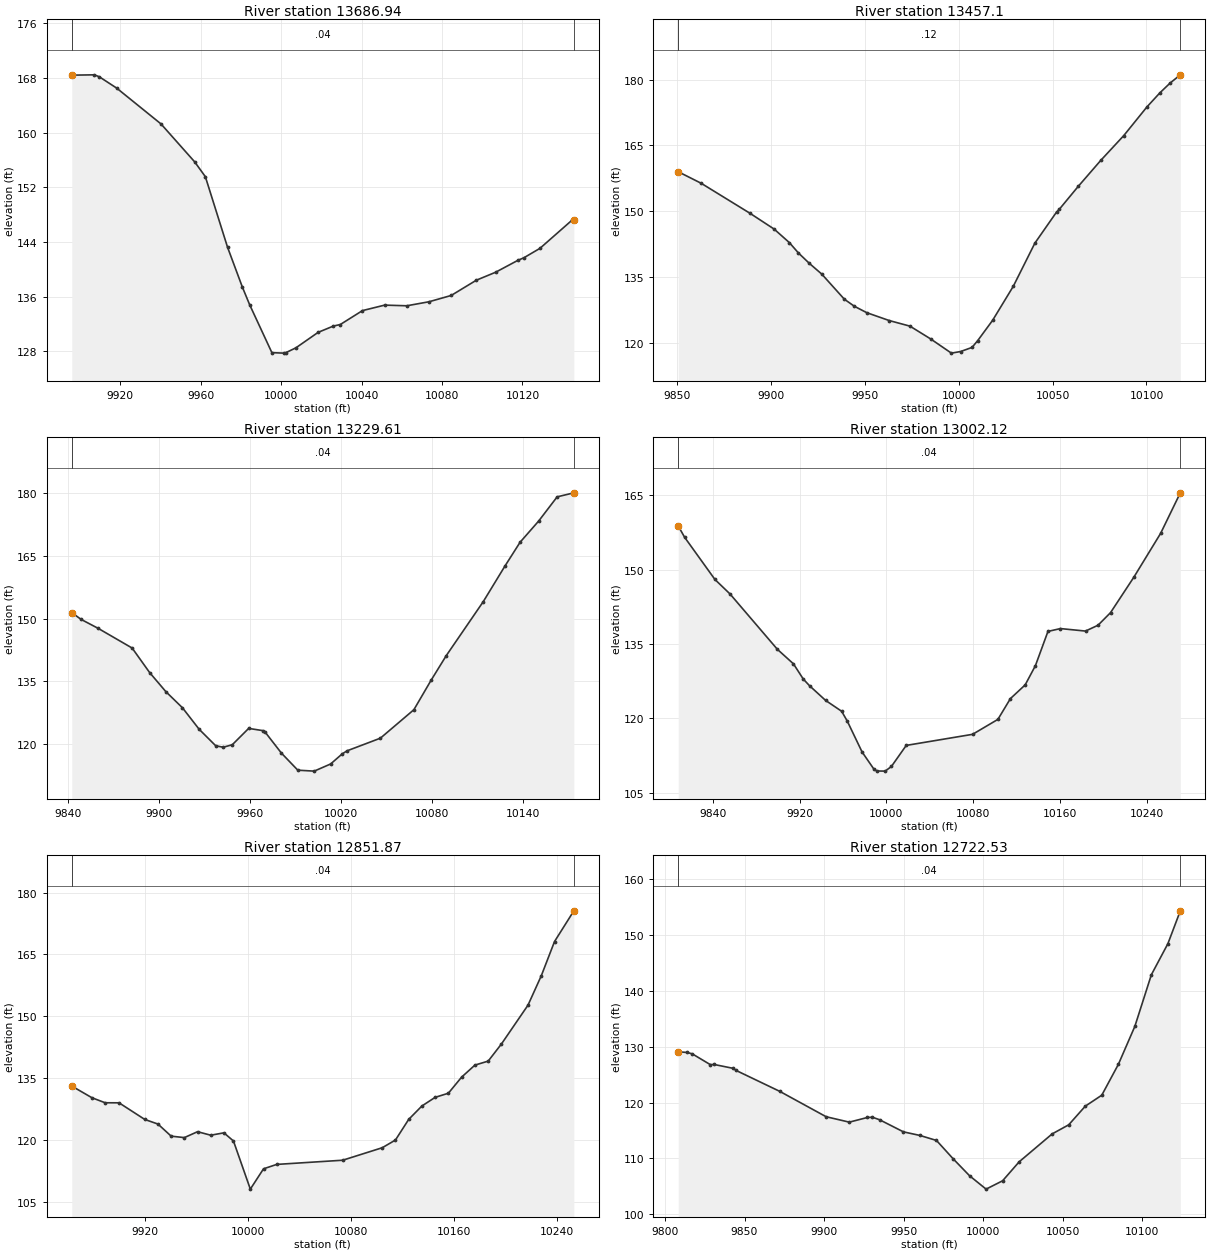
Type RM Length L Ch R = 1 ,13686.94,229.841800,229.841800,229.841800
XS GIS Cut Line= 4
860454.774848133 763960.79387942860548.583111107763917.130593866
860549.552389115763915.381165341860680.295681447 763854.54387942
#Sta/Elev= 29
9895.879168.40059907.157168.44959909.609168.15389918.188166.51259940.248161.2656
9957.004155.71239962.308 153.5469973.338143.22799980.702 137.4029984.369134.7888
9995.399127.795510001.35127.726810002.25127.780310007.36128.505710018.39130.7664
10025.96131.684410029.42131.913710040.45133.950610051.48134.751310062.51134.6554
10073.54 135.24410084.57 136.16510097.07138.396710106.63139.558710117.66141.2935
10120.77141.688910128.69143.056210144.47147.135210145.56147.2753
#Mann= 3 , 0 , 0
9895.879    0.04       09895.879    0.04       010145.56    0.04       0
#XS Ineff= 2 , 0
       0                10033.52       0
Bank Sta=9895.879,10145.56
Exp/Cntr=0.3,0.1

Type RM Length L Ch R = 1 , 13457.1,227.488400,227.488400,227.488400
XS GIS Cut Line= 6
860615.865879677764092.985645162860669.483008346764048.251592985
860704.395790453764025.056536997860764.382459255763997.515645959
860798.609578673 763977.97725251860839.280264725763948.430660949
#Sta/Elev= 30
9850.585158.97629862.813156.34629888.727149.52529901.671145.90049909.788142.8151
9914.614140.45519920.417 138.0889927.041 135.6389939.046129.92279944.364128.3133
9951.052126.83359962.999125.04369974.026123.77039985.054120.85479996.081117.6192
   10001117.983110007.09118.923410010.09 120.46410018.05125.099910029.05132.8518
10040.57142.705910052.08149.765710053.59150.4253 10063.6155.611410075.62161.5457
10087.94167.232610100.25173.753610107.13176.957610112.56179.180510118.03181.0732
#Mann= 3 , 0 , 0
9850.585    0.12       09850.585    0.12       010118.03    0.12       0
#XS Ineff= 2 , 0
       0                               0
Bank Sta=9850.585,10118.03
Exp/Cntr=0.3,0.1

Type RM Length L Ch R = 1 ,13229.61,227.488500,227.488500,227.488500
XS GIS Cut Line= 6
860669.562804295764288.459737486860716.217638407764264.513755066
860841.826164184 764210.91863748 860879.19749602764193.243449026
860917.327374074764171.650742337860963.848005272764138.641189978
#Sta/Elev= 30
9842.425151.48189848.536149.86879859.777147.72619882.257143.00079893.801137.1293
9904.499132.56469915.467128.69959926.435123.57249937.403119.6085 9942.37 119.264
9948.327119.85979959.137123.76989968.467123.23769969.946122.90329980.755117.8484
9991.564113.766510002.38113.541910013.21115.257210020.86 117.67510024.05118.4036
10046.02121.426810068.14 128.24610079.46135.281310089.52 141.20410113.93154.1277
10128.18162.6097 10138.2 168.32810150.42173.383810162.64179.188510173.66180.1521
#Mann= 3 , 0 , 0
9842.425    0.04       09842.425    0.04       010173.66    0.04       0
#XS Ineff= 2 , 0
       09960.957                       0
Bank Sta=9842.425,10173.66
Exp/Cntr=0.3,0.1

Type RM Length L Ch R = 1 ,13002.12,150.254900,150.254900,150.254900
XS GIS Cut Line= 6
860820.684955211764537.542701855  860864.0265464 764495.47501138
860953.457410929764397.805097724860984.382629672764359.799832692
861004.933527189764328.040694192861096.390845696764169.248838697
#Sta/Elev= 30
9808.168158.77619814.043156.49919841.987148.00349855.959145.06989899.627133.9216
9914.433131.00119923.454127.9439 9929.24 126.5969944.047123.64289958.854121.4548
9964.133119.42969977.693113.24949988.467 109.8419991.252109.4311    9999109.4008
10004.75 110.348 10018.4114.580610079.56116.8125 10102.9119.822410114.44124.0055
10128.06126.768610137.52130.650510149.06137.5393 10160.6138.110610183.68137.6083
10195.22138.782810206.76 141.31610228.24148.451410252.92157.2733 10271.1165.4497
#Mann= 3 , 0 , 0
9808.168    0.04       09808.168    0.04       0 10271.1    0.04       0
#XS Ineff= 2 , 0
       0                               0
Bank Sta=9808.168,10271.1
Exp/Cntr=0.3,0.1

Type RM Length L Ch R = 1 ,12851.87,129.338400,129.338400,129.338400
XS GIS Cut Line= 3
861056.742803445764590.326110033 861118.25667413764323.538990509
861147.091608533764210.439653665
#Sta/Elev= 30
 9862.96133.12579878.688130.29299888.951129.07929899.711 129.0729919.738125.0433
    9930123.92549940.263120.99629950.525120.64659960.787122.0759 9971.05 121.225
9981.312   121.89988.728119.817210001.84108.1685 10012.1113.088610022.36114.1531
10073.67115.167710104.46118.194810114.72120.061610124.99125.047110135.25128.2919
10145.56130.390810155.88131.3941 10166.2135.300110176.52138.203810186.84139.1684
10197.16143.3255 10217.8152.718910228.12159.820910238.44168.128310253.46175.5624
#Mann= 3 , 0 , 0
 9862.96    0.04       0 9862.96    0.04       010253.46    0.04       0
#XS Ineff= 2 , 0
       0                               0
Bank Sta=9862.96,10253.46
Exp/Cntr=0.3,0.1

Type RM Length L Ch R = 1 ,12722.53,228.047600,228.047600,228.047600
XS GIS Cut Line= 3
 861111.13950186764611.417293869861198.084511437764519.421720573
 861249.42258586764337.495800868
#Sta/Elev= 30
9808.321129.09239813.941128.9818 9817.15128.7315  9828.5126.7973 9830.91126.8258
9843.058126.12399844.669125.76299872.188122.00389901.293117.46329915.852116.4933
9927.226117.3282 9930.41117.37269934.901116.92189949.886114.75239960.277114.1072
9970.667113.21139981.058109.94729991.448106.885610001.84104.488610012.23105.9855
10022.62109.3812 10043.4 114.39210053.79116.016210064.18119.351910074.57121.3267
10084.96126.831610095.35 133.65610105.74 142.91310116.13148.481610123.93154.3655
#Mann= 3 , 0 , 0
9808.321    0.04       09808.321    0.04       010123.93    0.04       0
#XS Ineff= 2 , 0
       0                               0
Bank Sta=9808.321,10123.93
Exp/Cntr=0.3,0.1

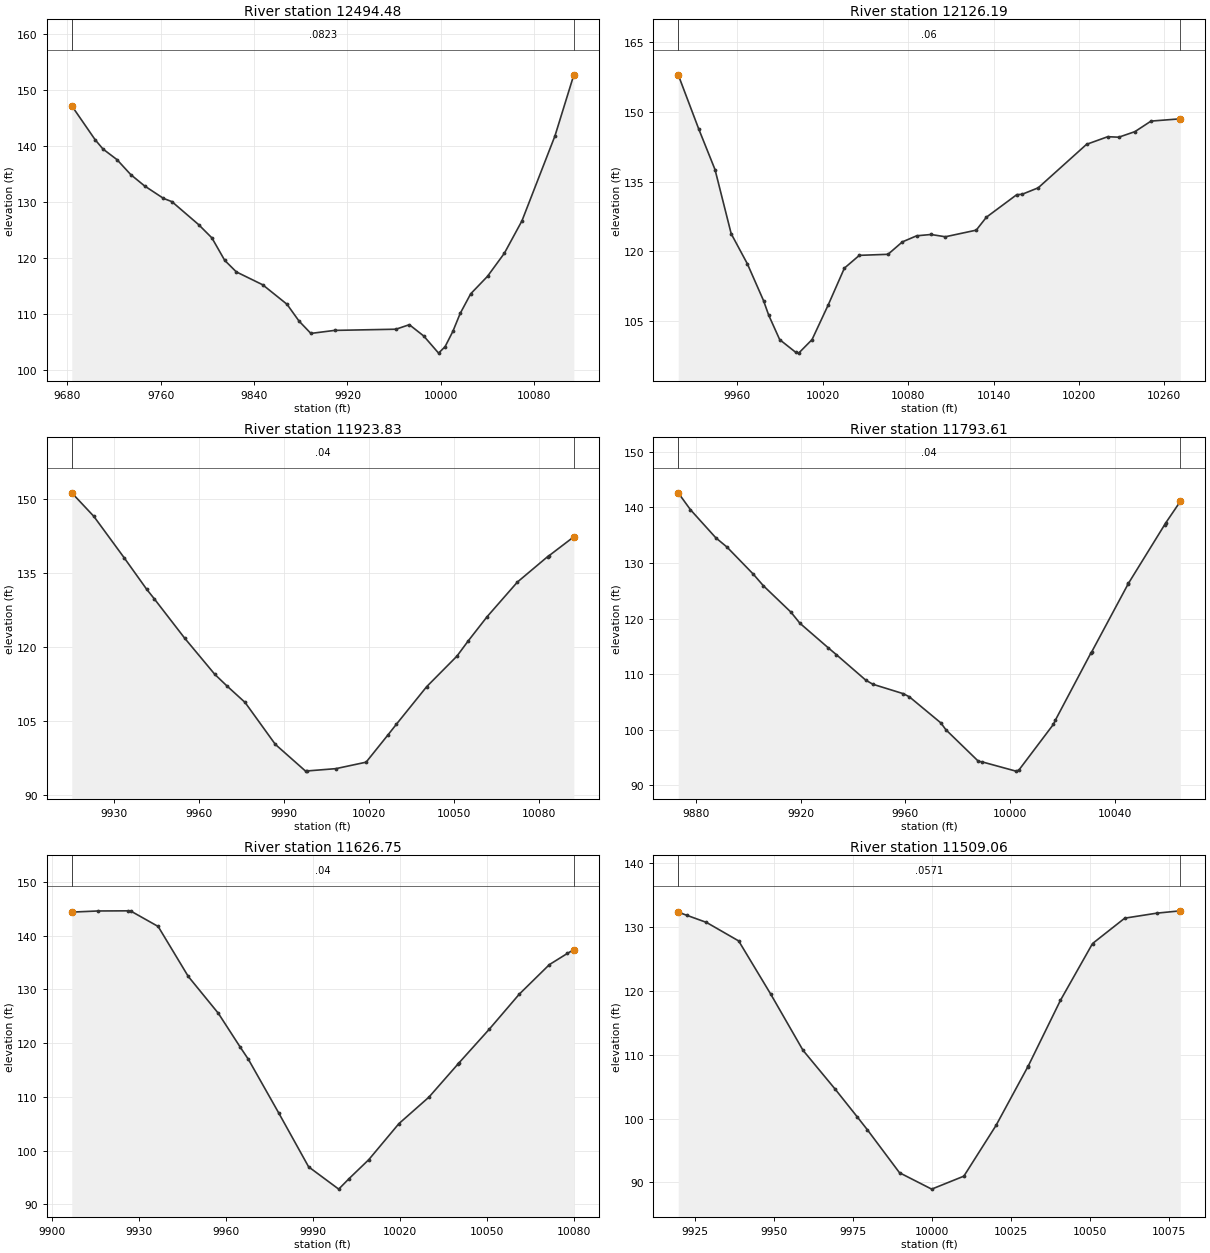
Type RM Length L Ch R = 1 ,12494.48,368.286500,368.286500,368.286500
XS GIS Cut Line= 6
861112.996256138764706.391278139861217.160583765764642.133574073
861255.891850557 764625.90345069861357.286815844764602.393206294
861378.006066729764590.619119503861473.917314284764492.726433492
#Sta/Elev= 30
9683.858147.20229703.874 141.1339710.619139.46729722.592 137.5749734.423134.8851
9746.254132.86459762.387130.64439769.649130.05349792.473125.95359803.885123.5699
 9814.85119.55439824.808117.48819847.378115.18549868.178111.7029 9878.47108.6994
9888.627106.48289908.941107.02529961.466107.23559972.968108.04369985.308106.0214
9998.008102.958110003.58104.115410010.21106.839710016.49110.0515 10025.5113.5672
10039.91116.700110054.31120.819210069.39126.614910097.69141.826910113.85152.7458
#Mann= 3 , 0 , 0
9683.858  0.0823       09683.858  0.0823       010113.85  0.0823       0
#XS Ineff= 2 , 0
       0                               0
Bank Sta=9683.858,10113.85
Exp/Cntr=0.3,0.1

Type RM Length L Ch R = 1 ,12126.19,202.368200,202.368200,202.368200
XS GIS Cut Line= 5
861232.252035563764805.171878802861338.394961084764747.934349155
861378.494919551764752.754687574   861426.548692764758.358882128
861553.168990184764691.072387345
#Sta/Elev= 30
9918.468157.90129932.951146.21379944.312137.56059955.674123.79839967.035117.3404
9978.396109.44229982.036106.31419989.758101.067110001.1298.32235 10003.198.17319
10012.48101.074710023.84108.5144 10035.2116.410910045.71 119.15910065.86119.3826
10075.93122.0457   10086123.355210096.07123.634910106.13 123.14510127.83124.5664
10134.99127.3464 10156.3132.180110160.05132.260510171.37133.650910205.34142.9825
10220.23144.621510227.99144.516410239.32145.707610250.64147.970610271.22  148.46
#Mann= 3 , 0 , 0
9918.468    0.06       09918.468    0.06       010271.22    0.06       0
#XS Ineff= 2 , 0
       0                               0
Bank Sta=9918.468,10271.22
Exp/Cntr=0.3,0.1

Type RM Length L Ch R = 1 ,11923.83,130.211100,130.211100,130.211100
XS GIS Cut Line= 2
861465.697124785 764892.25890403861528.124372602764726.364521203
#Sta/Elev= 24
9915.215151.18699922.971146.43989933.656138.06269941.629131.6527 9944.34129.6971
9955.025121.7482 9965.71 114.3779970.023112.01049976.394 108.6829987.079100.1762
9997.76394.747199998.41694.7894410008.4595.2495810019.1396.5623610026.81102.0653
10029.82104.2553 10040.5 111.86910051.19118.0638 10055.2121.173810061.87126.0802
10072.56133.100310083.24138.2567 10083.6138.387410092.47142.2688
#Mann= 3 , 0 , 0
9915.215    0.04       09915.215    0.04       010092.47    0.04       0
#XS Ineff= 2 , 0
       0                               0
Bank Sta=9915.215,10092.47
Exp/Cntr=0.3,0.1

Type RM Length L Ch R = 1 ,11793.61,166.869100,166.869100,166.869100
XS GIS Cut Line= 2
861531.641067682764915.028091073861669.266316039764781.160672289
#Sta/Elev= 30
9873.107142.62389873.147142.59439877.792139.58069887.489134.52889891.743132.8713
9901.831127.98299905.693125.89559916.173121.17519919.644119.15989930.515114.7278
9933.594113.50459944.857 108.9129947.544108.18769959.199106.48759961.495105.9264
9973.541101.23259975.445100.01019987.88394.334039989.39694.2127110002.2292.56068
10003.35 92.737910016.57100.9754 10017.3101.710710030.91113.810110031.25114.0386
 10045.2126.281410045.25126.326210059.15136.917710059.59137.2555 10065.1141.0793
#Mann= 3 , 0 , 0
9873.107    0.04       09873.107    0.04       0 10065.1    0.04       0
#XS Ineff= 2 , 0
       0                               0
Bank Sta=9873.107,10065.1
Exp/Cntr=0.3,0.1

Type RM Length L Ch R = 1 ,11626.75,117.681300,117.681300,117.681300
XS GIS Cut Line= 2
861556.295851324765010.390560928861723.131782582 764964.41513804
#Sta/Elev= 23
9906.825144.40889915.853  144.629926.226 144.6479927.115144.62059936.599141.7342
9946.972132.43449957.345125.55939964.756119.36949967.717116.9731 9978.09107.0627
9988.46396.963659998.83692.81296 10002.494.7676310009.2198.3078810019.58105.0098
10029.95109.956910040.04116.172610040.33116.3506 10050.7122.580110061.07129.1262
10071.44134.626510077.68136.724310079.88137.4172
#Mann= 3 , 0 , 0
9906.825    0.04       09906.825    0.04       010079.88    0.04       0
#XS Ineff= 2 , 0
       0                               0
Bank Sta=9906.825,10079.88
Exp/Cntr=0.3,0.1

Type RM Length L Ch R = 1 ,11509.06,163.169300,163.169300,163.169300
XS GIS Cut Line= 2
861616.215609816 765105.49774711 861772.27659735765076.064085286
#Sta/Elev= 20
9919.695132.25499922.381131.76929928.634130.6509 9938.81127.75849948.987119.4106
9959.163110.66079969.339104.58599976.337100.24249979.51698.242689989.69291.51931
9999.86888.9600910010.0490.9868310020.2298.9180510030.29108.0996 10030.4108.1947
10040.57118.450610050.75127.352110060.93131.3147 10071.1132.101410078.51132.4627
#Mann= 3 , 0 , 0
9919.695  0.0571       09919.695  0.0571       010078.51  0.0571       0
#XS Ineff= 2 , 0
       0                               0
Bank Sta=9919.695,10078.51
Exp/Cntr=0.3,0.1

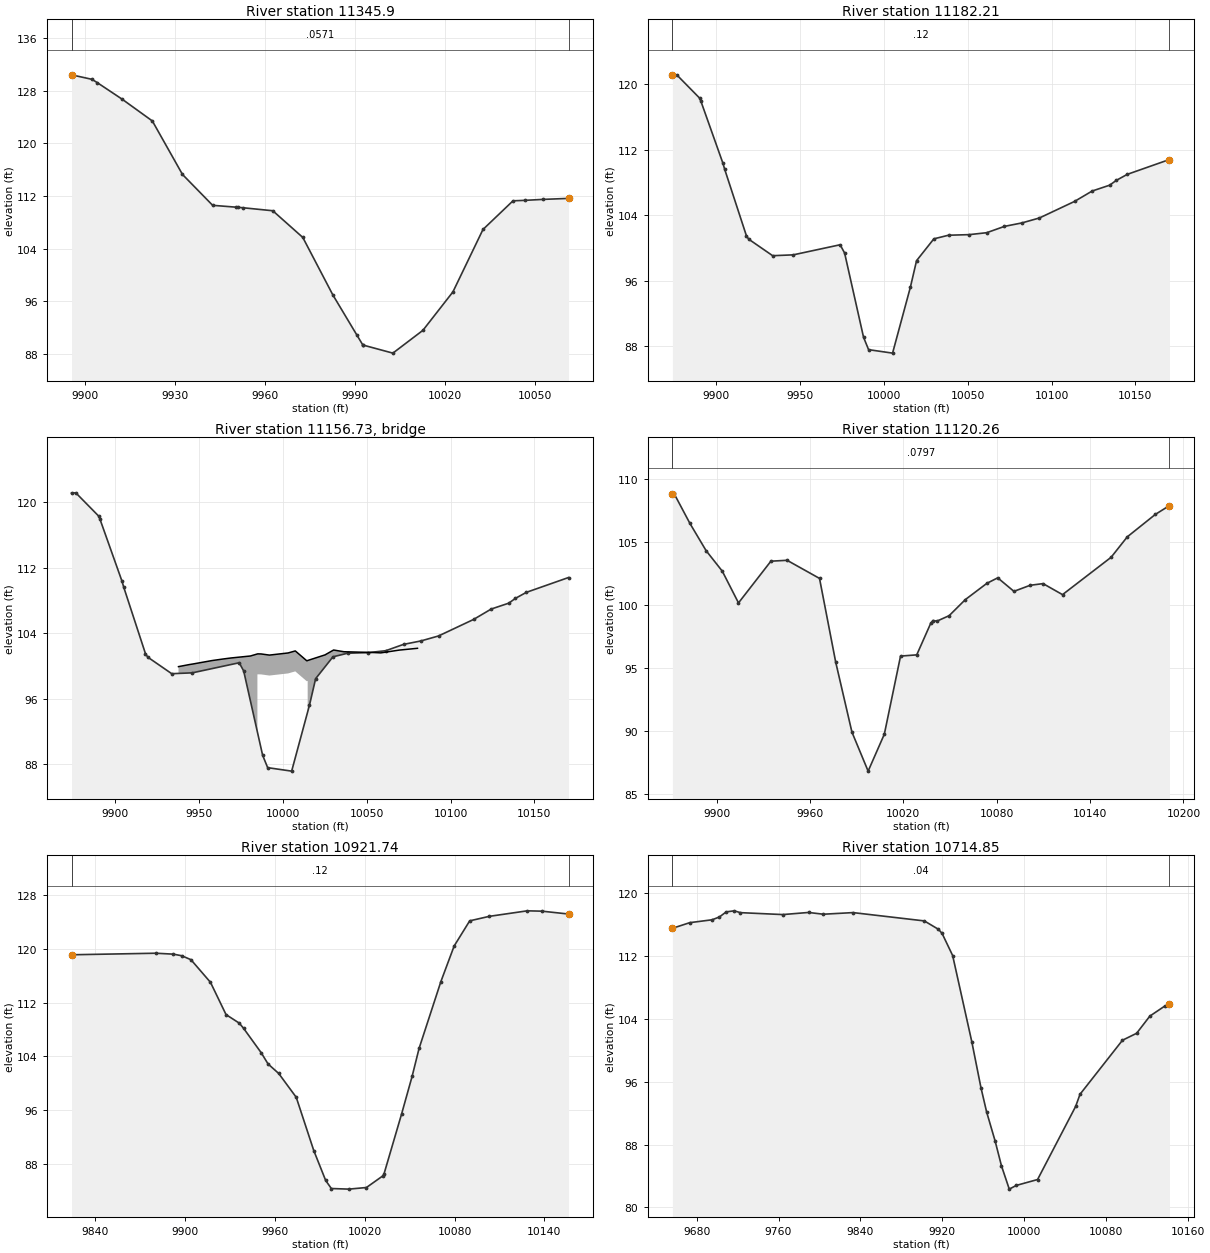
Type RM Length L Ch R = 1 , 11345.9,163.680900,163.680900,163.680900
XS GIS Cut Line= 6
861598.318655577765261.237101635861606.796810083765259.524226347
861652.620155909765255.026970453861695.018802856765253.591933702
861748.898261607765251.202328078861763.364036031765249.135698636
#Sta/Elev= 24
9895.559130.41999902.375129.73579904.208129.21469912.451126.71119922.499123.4077
9932.547115.27979942.595110.59169950.252110.31549950.997110.28689952.633110.2256
 9962.64109.76679972.646105.70979982.65396.983339990.67790.870649992.658 89.3652
9992.67789.3628910002.6788.1326610012.6891.5971410022.6997.44282 10032.7106.9214
10042.71111.276210046.61111.345410052.77111.493310061.22111.6434
#Mann= 3 , 0 , 0
9895.559  0.0571       09895.559  0.0571       010061.22  0.0571       0
#XS Ineff= 2 , 0
       0                               0
Bank Sta=9895.559,10061.22
Exp/Cntr=0.3,0.1

Type RM Length L Ch R = 1 ,11182.21,61.953600,61.953600,61.953600
XS GIS Cut Line= 3
861623.208744746765506.559535905861732.498208898765394.706852525
861774.521360443765260.982745506
#Sta/Elev= 30
9873.804121.13069876.367 121.1629889.965118.32779890.676117.99999903.946110.3453
9904.985109.61159917.927101.50069919.294101.07689933.60399.055079945.88999.15904
9973.851100.39199976.52999.383819987.83289.087329990.83887.5717410005.1587.14757
10015.7995.2144210019.4698.4461910029.78101.115110038.53101.557710050.84101.6291
10061.32101.866310071.89102.638110082.29103.060210092.77103.666810113.74105.6913
10124.22106.9586 10134.7107.6763 10138.6 108.25610145.18 108.99710170.36110.8119
#Mann= 3 , 0 , 0
9873.804    0.12       09873.804    0.12       010170.36    0.12       0
#XS Ineff= 2 , 0
       0 9971.98                       0
Bank Sta=9873.804,10170.36
Exp/Cntr=0.3,0.1

Type RM Length L Ch R = 3 ,11156.73,,,
BEGIN DESCRIPTION:
END DESCRIPTION:
Bridge Culvert--1,0,-1,-1, 0
Deck Dist Width WeirC Skew NumUp NumDn MinLoCord MaxHiCord MaxSubmerge Is_Ogee
20.976800,20.000000,2.6,0, 27, 27, , , 0.95, 0, 0,0,,
 9937.64 9944.05 9946.16 9957.62 9964.51 9969.08 9980.55 9984.72 9984.72 9984.98
 9986.91 9991.8710003.0310007.3210014.1910014.7210014.7210025.2810025.3510030.17
10036.3410047.3410054.2110058.3410069.3310078.2410080.22
   99.92  100.17  100.24  100.66  100.86  100.98  101.22  101.47  101.47  101.48
  101.47  101.33  101.59  101.84  100.63  100.67  100.67  101.37  101.39  101.95
  101.74  101.68  101.64  101.60  101.94  102.12  102.16
 -900.08 -899.83 -899.76 -899.34 -899.14 -899.02 -898.78 -898.53   98.97   98.98
   98.97   98.83   99.09   99.34   98.13   98.17 -899.33 -898.63 -898.61 -898.05
 -898.26 -898.32 -898.36 -898.40 -898.06 -897.88 -897.84
 9937.64 9944.05 9946.16 9957.62 9964.51 9969.08 9980.55 9984.08 9984.08 9984.98
 9986.91 9991.8710003.0310007.3210014.0810014.0810014.1910025.2810025.3510030.17
10036.3410047.3410054.2110058.3410069.3310078.2410080.22
   99.92  100.17  100.24  100.66  100.86  100.98  101.22  101.43  101.43  101.48
  101.47  101.33  101.59  101.84  100.65  100.65  100.63  101.37  101.39  101.95
  101.74  101.68  101.64  101.60  101.94  102.12  102.16
 -900.08 -899.83 -899.76 -899.34 -899.14 -899.02 -898.78 -898.57   98.93   98.98
   98.97   98.83   99.09   99.34   98.15 -899.35 -899.37 -898.63 -898.61 -898.05
 -898.26 -898.32 -898.36 -898.40 -898.06 -897.88 -897.84
BR Coef=-1 , 0 , 0 ,, 0 ,,,0.8,0,1,0,
WSPro=,,,, 1 ,,,, 0 ,,,, 0 ,,,,-1 ,-1 ,-1 , 0 , 0 , 0 , 0 , 0
BC Design=,, 0 ,, 0 ,,,,,,

Type RM Length L Ch R = 1 ,11120.26,198.515900,198.515900,198.515900
XS GIS Cut Line= 3
861718.709428783765575.766526208861766.109219094765412.532279717
861807.504101381765268.963544435
#Sta/Elev= 30
9871.626108.86549872.424108.92419882.837 106.501 9893.25 104.3359903.663102.7041
9914.076100.18379934.902103.49729945.315103.56689966.141102.12919976.55495.47492
9986.96889.928189997.381 86.827910007.7989.7604210018.2195.9614710028.6296.05892
10037.62 98.568810039.0398.78334 10041.698.7372310049.4499.1709910059.85100.4478
10073.69101.738810080.66102.174410091.07101.102110101.48101.582110109.79101.7157
10122.29100.840910153.52103.806410163.92105.429510181.98107.214210191.02107.9107
#Mann= 3 , 0 , 0
9871.626  0.0797       09871.626  0.0797       010191.02  0.0797       0
#XS Ineff= 2 , 0
       09958.661                       0
Bank Sta=9871.626,10191.02
Exp/Cntr=0.3,0.1

Type RM Length L Ch R = 1 ,10921.74,206.897500,206.897500,206.897500
XS GIS Cut Line= 2
861856.755790918765613.061514964862029.316445356765329.824345462
#Sta/Elev= 30
9824.436119.14399880.714119.37429892.424119.23659897.941118.99939904.134118.4108
9917.162115.04069927.553110.23349936.382108.96229939.263108.18819950.973104.5691
9955.602102.87999962.683101.47139974.39297.917719986.10289.978369994.04285.52868
9997.81284.3343110009.5284.2433210021.2384.4833910032.4886.2640310032.9486.49435
10044.6595.39881 10051.7101.026810056.36   105.210070.92115.158110079.78120.4577
10090.14124.1964 10103.2124.866110128.58125.688410138.33125.6383 10156.1125.2101
#Mann= 3 , 0 , 0
9824.436    0.12       09824.436    0.12       0 10156.1    0.12       0
#XS Ineff= 2 , 0
       0                               0
Bank Sta=9824.436,10156.1
Exp/Cntr=0.3,0.1

Type RM Length L Ch R = 1 ,10714.85,357.229000,357.229000,357.229000
XS GIS Cut Line= 2
861757.005686688765896.684397185862108.198102577765561.791702701
#Sta/Elev= 30
9656.416115.49449673.347116.21229695.098116.57689702.327116.93849708.916117.5827
9716.818117.71699722.733117.48579764.187117.2401 9789.27117.5092 9803.76117.2858
9832.741117.49169902.365116.43419916.183115.36289919.683114.84559930.001112.0335
9948.664101.09489957.63795.231299963.15492.151519971.45588.456119977.645 85.3017
9985.27382.330889992.13582.8016110012.9183.55151 10050.192.8492310054.36 94.3927
10095.82 101.26410109.63102.146410122.55104.332910137.27105.620910141.69105.8244
#Mann= 3 , 0 , 0
9656.416    0.04       09656.416    0.04       010141.69    0.04       0
#XS Ineff= 2 , 0
       0                               0
Bank Sta=9656.416,10141.69
Exp/Cntr=0.3,0.1

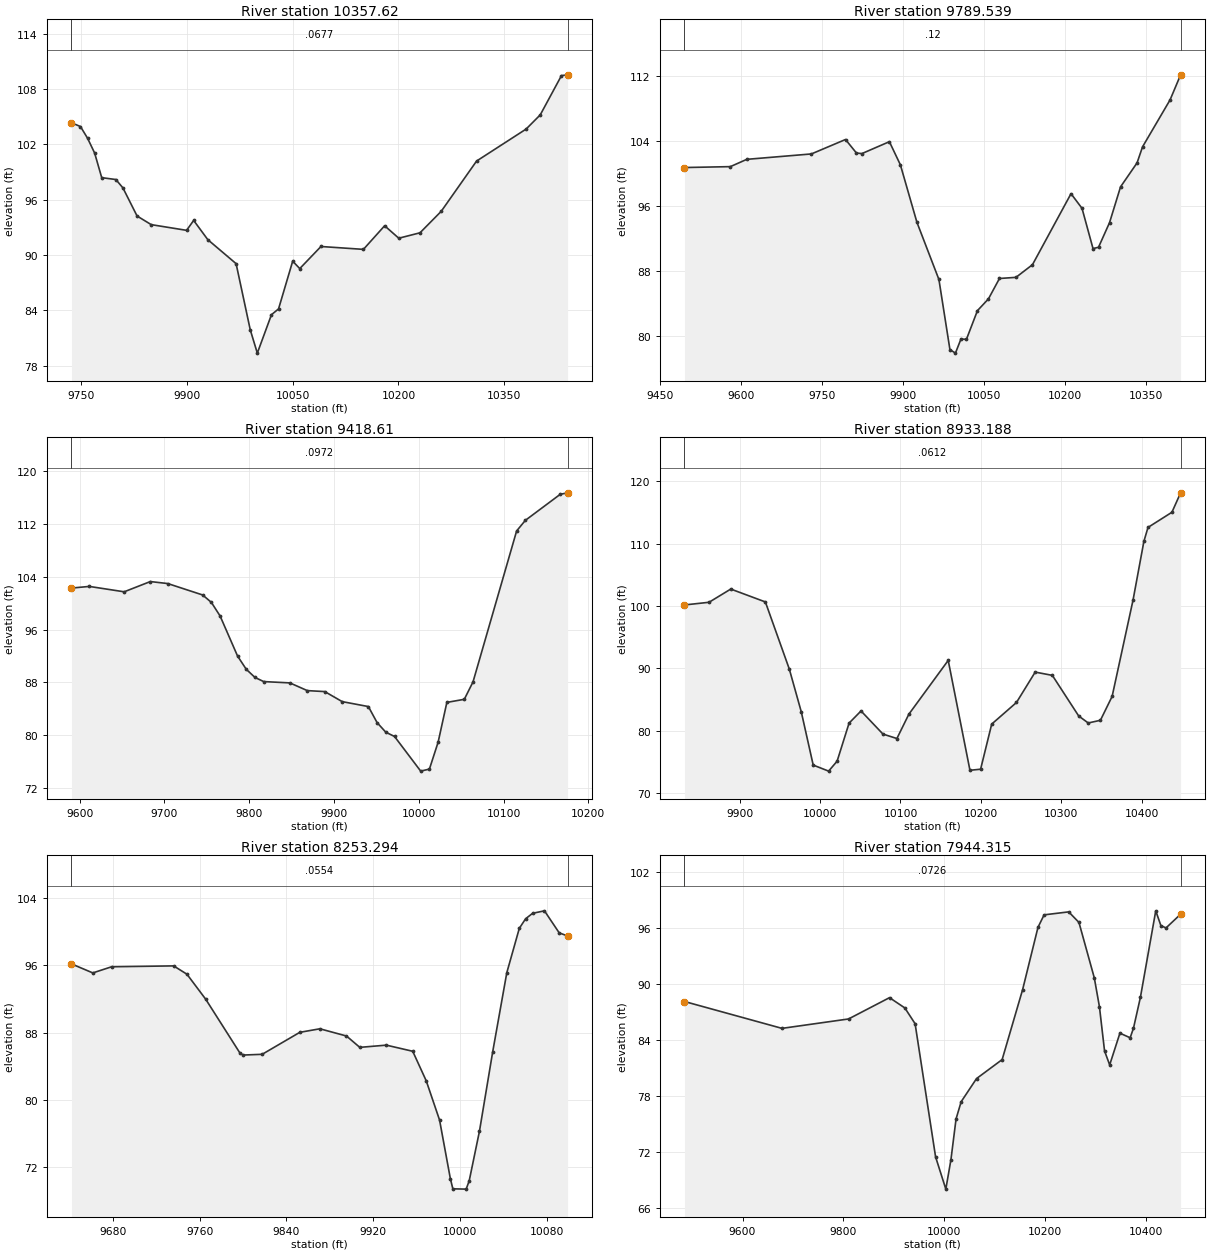
Type RM Length L Ch R = 1 ,10357.62,568.079200,568.079200,568.079200
XS GIS Cut Line= 2
862201.036257372766197.758003398862155.859776348765496.328665941
#Sta/Elev= 30
9736.733104.34549749.518103.92399759.538102.65889769.559101.0517 9779.5898.38416
9799.62198.180449809.64297.271339829.68394.223019849.72593.287499899.82892.66879
9909.849 93.74449929.89191.656979969.97389.055439990.01581.8842410000.0479.34977
10020.0883.51961 10030.184.1441110050.1489.3229610060.1688.5196610090.22 90.9163
10150.3590.6047310180.4193.1651610200.45 91.814910230.5192.4015910260.5794.73171
10310.68100.185210380.82 103.65310400.86105.192310430.93109.453510439.62109.5378
#Mann= 3 , 0 , 0
9736.733  0.0677       09736.733  0.0677       010439.62  0.0677       0
#XS Ineff= 2 , 0
       0 9957.45                       0
Bank Sta=9736.733,10439.62
Exp/Cntr=0.3,0.1

Type RM Length L Ch R = 1 ,9789.539,370.928600,370.928600,370.928600
XS GIS Cut Line= 3
862545.847239185766108.653266825 862481.02279019765741.397548661
 862375.48275767765205.862410468
#Sta/Elev= 30
9495.228100.74219580.174100.85299610.638101.74859730.221102.41179793.421 104.184
 9813.73102.52049823.884102.45829874.681103.91729895.066101.07279925.64394.02372
9966.41386.992639986.79778.38572 9996.9977.9492810007.18 79.673410017.37 79.6434
10037.7683.1677110058.1484.6126910078.5387.1165610109.11 87.255510139.6888.81139
10211.0397.5316910231.4195.73361 10251.890.7876410261.99 90.952710282.3893.97462
10302.7698.3679810333.34101.314310343.53103.287610394.49109.0515   10414112.1281
#Mann= 3 , 0 , 0
9495.228    0.12       09495.228    0.12       0   10414    0.12       0
#XS Ineff= 2 , 0
       0                               0
Bank Sta=9495.228,10414
Exp/Cntr=0.3,0.1

Type RM Length L Ch R = 1 , 9418.61,485.422600,485.422600,485.422600
XS GIS Cut Line= 2
 862717.94177207765715.427792071862581.153700597 765146.57155219
#Sta/Elev= 30
9590.425102.31829611.435102.56969652.575101.7539 9683.43 103.308    9704103.0034
 9745.14101.27239755.425100.14659765.71198.084019786.281 92.01479796.56690.00023
9806.85188.763529817.13688.139019847.991  87.9399868.56186.768759889.13186.62275
9909.70185.099449940.55684.351329950.84181.916779961.12680.459559971.411 79.8141
10002.2774.5595210012.5574.8692810022.8478.9591510033.1284.9821110053.6985.45127
10063.9888.09659 10115.4110.982310125.69112.589810166.83116.5387 10175.5116.7634
#Mann= 3 , 0 , 0
9590.425  0.0972       09590.425  0.0972       0 10175.5  0.0972       0
#XS Ineff= 2 , 0
       0                               0
Bank Sta=9590.425,10175.5
Exp/Cntr=0.3,0.1

Type RM Length L Ch R = 1 ,8933.188,679.893400,679.893400,679.893400
XS GIS Cut Line= 2
862767.349783482765747.576734146863182.264688405 765291.24463084
#Sta/Elev= 30
9831.516100.1625 9862.03100.59039889.061102.70859932.076100.64489961.80689.90188
 9976.6783.064599991.53574.51797 10010.773.5482310021.2675.1428510036.1381.23813
10050.99 83.184710078.2879.4801810095.5978.7706410110.4582.6657210159.3791.28256
 10186.473.6820710199.6473.8553610213.44  81.08110244.2484.54341 10267.589.40836
10288.8388.8847910321.5682.3850110333.4281.2598210348.5981.6914910363.1585.51592
10389.14100.940510402.65110.355710407.75112.580710437.48115.008510448.28118.1206
#Mann= 3 , 0 , 0
9831.516  0.0612       09831.516  0.0612       010448.28  0.0612       0
#XS Ineff= 2 , 0
       0                10141.32       0
Bank Sta=9831.516,10448.28
Exp/Cntr=0.3,0.1

Type RM Length L Ch R = 1 ,8253.294,308.979600,308.979600,308.979600
XS GIS Cut Line= 2
863103.662522584765861.860123066863367.294233861765488.700153078
#Sta/Elev= 30
9642.03596.146219661.68495.076799679.01495.805659736.14295.909249748.38594.92144
9765.66891.954719797.36185.537429800.32985.33672 9817.6685.423129852.32188.03072
9870.82488.449179895.31287.592969907.556 86.24779932.04386.510249956.30585.78315
9968.77582.270649981.01977.626349990.96770.675189993.26369.4718610005.5169.43439
 10008.370.4105710017.7576.2954710029.9985.7469410042.9695.1097710054.48100.3687
10060.29101.500910066.73102.146710077.62102.439810091.2199.8251910098.9399.45785
#Mann= 3 , 0 , 0
9642.035  0.0554       09642.035  0.0554       010098.93  0.0554       0
#XS Ineff= 2 , 0
       0                               0
Bank Sta=9642.035,10098.93
Exp/Cntr=0.3,0.1

Type RM Length L Ch R = 1 ,7944.315,290.517200,290.517200,290.517200
XS GIS Cut Line= 2
863394.274586188766325.405667108863560.825012194765356.455613141
#Sta/Elev= 30
9484.98688.148879678.18485.268649810.09186.276799891.26488.562029921.70487.45655
9941.99785.767169982.58471.4904510002.8868.0296210013.0271.1924110023.17 75.5619
10033.3277.4075610063.7679.8848910114.4981.9205310155.0889.4261410185.5296.10509
10197.64 97.4405 10246.497.7606210266.6996.6298910297.1390.6819810307.2887.58934
10317.4282.8500610327.5781.3487610347.8684.7536310368.1684.2612410374.7385.27952
10388.4588.5841110418.8997.8728610429.0496.2911110439.1896.0368810468.1597.50955
#Mann= 3 , 0 , 0
9484.986  0.0726       09484.986  0.0726       010468.15  0.0726       0
#XS Ineff= 2 , 0
       0                10153.38       0
Bank Sta=9484.986,10468.15
Exp/Cntr=0.3,0.1

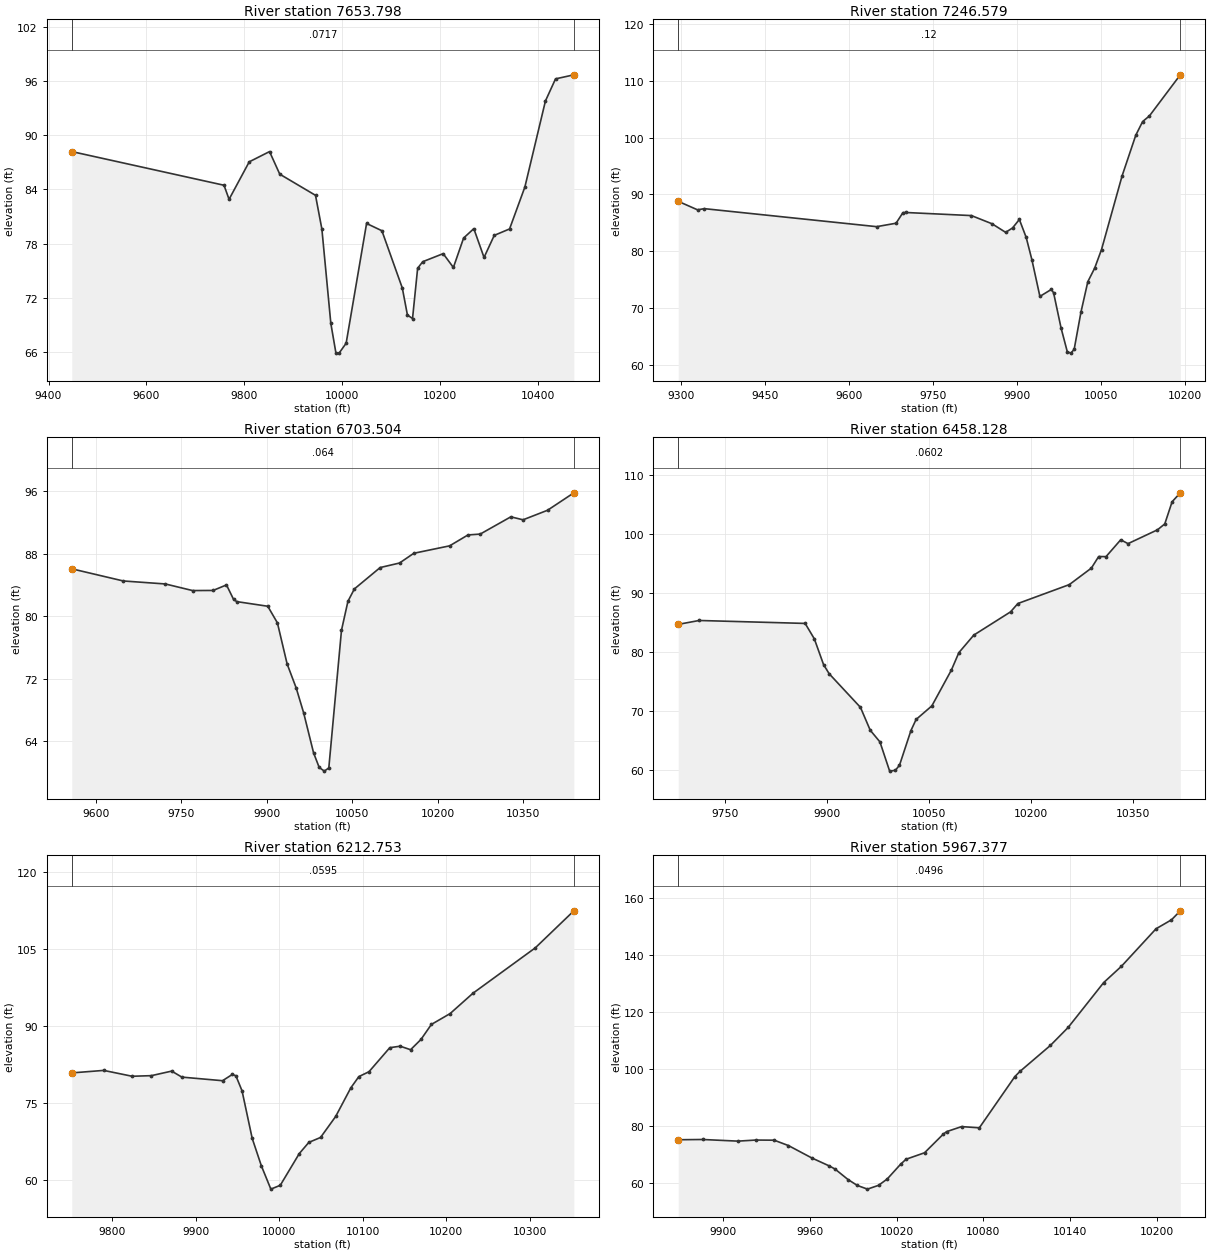
Type RM Length L Ch R = 1 ,7653.798,407.219000,407.219000,407.219000
XS GIS Cut Line= 3
863720.983444998766346.976612157 863812.03250841765977.192514996
863628.483710543765359.137017848
#Sta/Elev= 30
9447.49788.193369758.49384.462729768.79182.905449809.98687.056019851.47688.19055
9872.33985.690959945.36183.347569958.40679.603649976.65669.169479987.088 65.8827
9993.53265.8745210007.9566.9692410049.6880.2319910080.9779.42608 10122.773.07744
10133.1370.0943510143.5669.7037110153.9975.2742910164.43 75.998310206.1576.88928
10227.02 75.357810247.8878.6180610268.7479.6573310289.6176.4686710310.4778.91302
10341.7679.6239810373.0684.2720610415.0493.7956310435.6596.2415810473.0696.68951
#Mann= 3 , 0 , 0
9447.497  0.0717       09447.497  0.0717       010473.06  0.0717       0
#XS Ineff= 2 , 0
       0                10139.46       0
Bank Sta=9447.497,10473.06
Exp/Cntr=0.3,0.1

Type RM Length L Ch R = 1 ,7246.579,543.075000,543.075000,543.075000
XS GIS Cut Line= 2
863750.572492289766383.162346955864267.896954404765649.943640241
#Sta/Elev= 30
9295.122 88.78679329.58887.293289341.82787.497569649.72184.329799684.41384.93351
9696.74386.797829701.75986.823189819.12886.279149855.84384.84295 9880.3283.32932
9892.56484.096689904.79785.593959917.03682.427739927.25678.489699941.51372.05671
9961.94873.28536 9965.9972.690279979.29466.520579990.46762.32598 9996.6462.07378
10002.7162.7148810014.9469.3074510027.1874.6496810039.4277.0318910051.66 80.3084
10088.3793.2499310112.85100.412910125.09102.819610137.33103.827510192.47111.0498
#Mann= 3 , 0 , 0
9295.122    0.12       09295.122    0.12       010192.47    0.12       0
#XS Ineff= 2 , 0
       0                               0
Bank Sta=9295.122,10192.47
Exp/Cntr=0.3,0.1

Type RM Length L Ch R = 1 ,6703.504,245.375400,245.375400,245.375400
XS GIS Cut Line= 6
864179.193045026766477.937818124864238.466583073766397.186886231
864376.125451834 766193.47935171864438.401818972 766118.68251265
864590.106275084766038.140222605864837.987866572765940.527850245
#Sta/Elev= 30
9557.43186.051419647.90984.498339721.78884.115869769.59283.271789805.60683.28652
 9829.14 83.99319841.62182.140079847.215 81.85959901.645 81.26729918.584 79.1408
9935.61373.896799951.59470.815029964.58667.662249982.09762.528289991.94760.66778
   1000160.1950610008.8560.6065410031.1178.2006210042.4481.9024110053.7683.48053
10099.0586.2139310133.0186.7903310158.1388.0376910221.0188.9870910253.2590.37969
10274.7590.4904910328.4892.6944310349.9892.3154210392.9793.5338710439.1795.76286
#Mann= 3 , 0 , 0
9557.431   0.064       09557.431   0.064       010439.17   0.064       0
#XS Ineff= 2 , 0
       0                               0
Bank Sta=9557.431,10439.17
Exp/Cntr=0.3,0.1

Type RM Length L Ch R = 1 ,6458.128,245.375400,245.375400,245.375400
XS GIS Cut Line= 6
864348.519612838766536.315480243864415.424133648766472.171029481
864541.919260104766356.879392623864618.875144672766279.055848479
 864678.52794701766251.684857422864956.169686963766137.766677498
#Sta/Elev= 30
9681.30984.706349712.10985.364799868.13484.867099881.66582.251289895.19577.90742
9903.40376.36067 9949.5670.658579963.88266.799869978.20364.819239992.52559.87093
   1000160.01629   1000760.8686310023.8766.7444610031.4268.6125510054.6270.90993
10083.3776.9714110094.3779.9172110116.3782.8912710170.4986.82437 10181.388.23546
10256.9691.4337910289.3994.22363 10300.296.18792   1031196.1692410332.6299.01754
10343.4398.3690210386.67100.703710397.48101.701510408.29105.458510420.36106.9675
#Mann= 3 , 0 , 0
9681.309  0.0602       09681.309  0.0602       010420.36  0.0602       0
#XS Ineff= 2 , 0
       0                               0
Bank Sta=9681.309,10420.36
Exp/Cntr=0.3,0.1

Type RM Length L Ch R = 1 ,6212.753,245.375400,245.375400,245.375400
XS GIS Cut Line= 6
864507.816366921 766657.73698006864557.644085509766620.876442895
 864656.45985604766552.303736496864746.901935563766501.543344036
864801.782863167766465.186873109865002.048289369766316.799936374
#Sta/Elev= 30
9751.83380.878499790.06481.36745 9824.1280.22544 9847.1180.344019871.45481.23188
9883.62680.060569932.314 79.3605 9944.0480.580259948.32880.318089955.68977.38576
 9967.8268.140579978.84762.763249990.16758.2402110001.4458.9857710024.2565.17683
10035.6667.3471510049.68 68.306210067.7972.39943 10085.977.9674910095.5380.16184
10107.6781.1113110132.5685.7927710145.0186.0831110157.4585.39593 10169.987.40047
10182.3490.3197410204.7692.4339510232.1396.39977 10306.8105.245610352.91112.4527
#Mann= 3 , 0 , 0
9751.833  0.0595       09751.833  0.0595       010352.91  0.0595       0
#XS Ineff= 2 , 0
       0                               0
Bank Sta=9751.833,10352.91
Exp/Cntr=0.3,0.1

Type RM Length L Ch R = 1 ,5967.377,245.375400,245.375400,245.375400
XS GIS Cut Line= 6
864791.155612417766760.004649785864833.173427998766730.484014902
864882.882216994   766691.220584864907.238706417766668.873252888
864944.399970744766638.944093649865069.059862308766551.661815017
#Sta/Elev= 30
9868.68775.107519885.54375.194879910.03374.619259922.36974.998379935.11274.95132
9945.02273.054659961.15668.709919973.342 65.88329977.28964.796969986.23261.12783
9992.69859.039589999.72457.7461910007.4159.08605 10013.461.3050210022.62 66.4671
10026.4168.2436710039.2570.5257810052.0977.0102210054.5177.95309 10064.979.72637
 10077.279.30058 10101.897.3142810105.2899.1082110126.41 108.26710138.71114.5933
10163.31 130.36310175.61136.096810199.57149.281510210.26152.426110216.37155.5868
#Mann= 3 , 0 , 0
9868.687  0.0496       09868.687  0.0496       010216.37  0.0496       0
#XS Ineff= 2 , 0
       0                               0
Bank Sta=9868.687,10216.37
Exp/Cntr=0.3,0.1