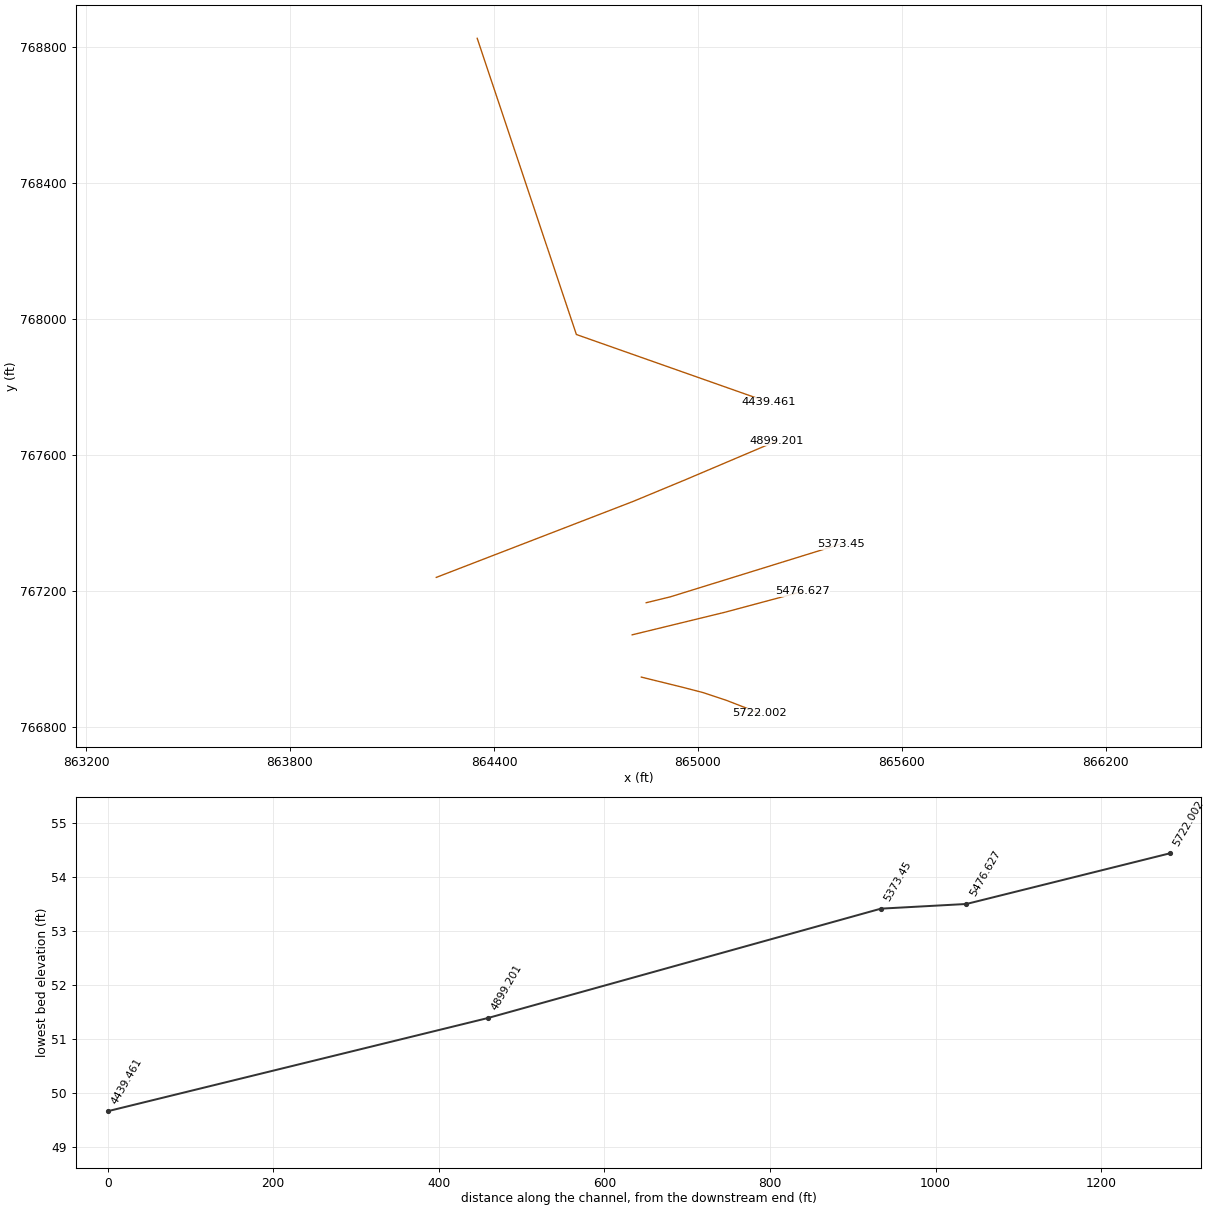
HEC-RAS study 9801_ras.prj: 9801

--- 9801_ras.g01 (geometry) --- (continued)

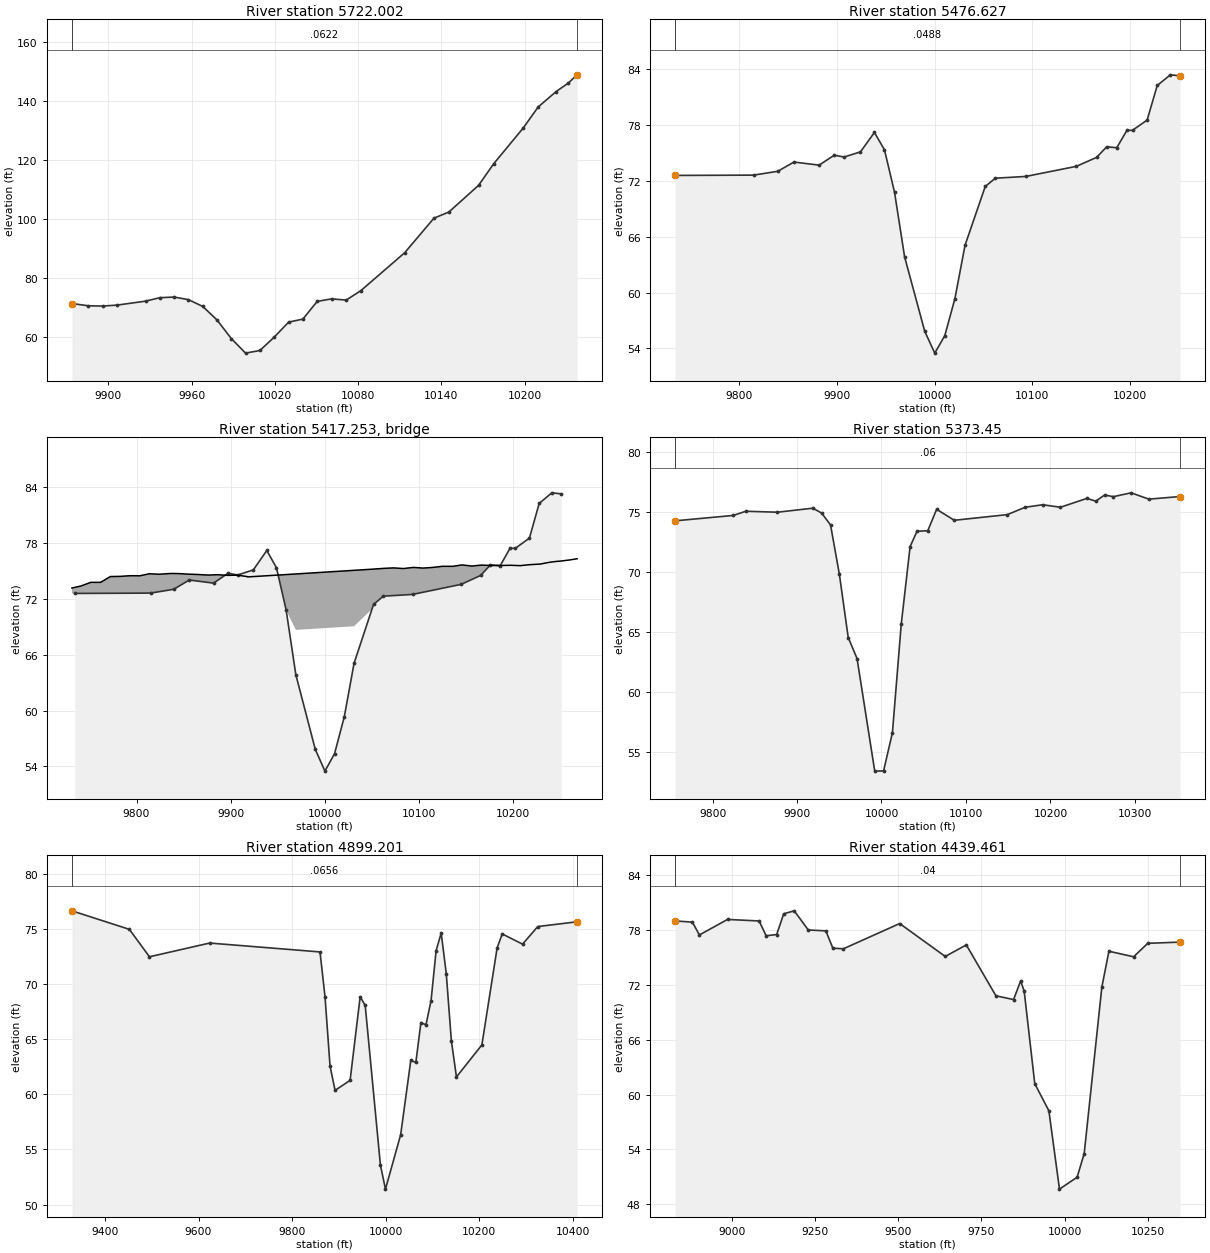
Type RM Length L Ch R = 1 ,5722.002,245.375400,245.375400,245.375400
XS GIS Cut Line= 6
864833.540574005766945.729667547864955.111844114766915.758405633
865014.355199452766900.422408115865083.510145845766877.511593738
 865162.56544137766846.805457926865180.935571872766839.031369895
#Sta/Elev= 30
9873.78471.278279885.64870.508739895.98970.420179906.27870.741489926.85872.08764
9937.14773.264179947.437 73.46979957.72672.602289968.01670.299299978.30665.71119
9988.59559.401369998.88554.4385110009.2255.3362710019.5559.8687610029.8864.94963
 10040.266.0062510050.53 72.005510060.8872.8598810071.4172.4467910081.9475.64436
10113.5588.5257910134.65100.268810145.37 102.33510166.83111.426410177.56118.6649
10199.01130.901810209.74138.016210222.49143.183410231.36146.1026 10237.8148.9288
#Mann= 3 , 0 , 0
9873.784  0.0622       09873.784  0.0622       0 10237.8  0.0622       0
#XS Ineff= 2 , 0
       0                               0
Bank Sta=9873.784,10237.8
Exp/Cntr=0.3,0.1

Type RM Length L Ch R = 1 ,5476.627,103.176900,103.176900,103.176900
XS GIS Cut Line= 3
864806.692072943767070.114838892865078.856099774767136.351055173
865307.644810032767197.592835572
#Sta/Elev= 30
9734.28972.561069814.88372.595359839.52773.006859856.05173.998599881.81673.66343
9897.21874.72799 9907.5174.536559924.10575.090159938.38677.167549948.67875.31163
9958.96970.761719969.26163.834149989.84555.8565710000.1453.5028110010.4355.38714
10020.7659.3489310031.1165.0690710051.8171.3803910062.1772.2639410093.22 72.4526
10144.9873.5347310165.6974.4931910176.0475.6243310186.39 75.535410196.7477.38987
10202.5477.4062710217.4578.49704 10227.882.2117110241.2183.3511110251.2483.24258
#Mann= 3 , 0 , 0
9734.289  0.0488       09734.289  0.0488       010251.24  0.0488       0
#XS Ineff= 2 , 0
       0                               0
Bank Sta=9734.289,10251.24
Exp/Cntr=0.3,0.1

Type RM Length L Ch R = 3 ,5417.253,,,
BEGIN DESCRIPTION:
END DESCRIPTION:
Bridge Culvert--1,0,-1,-1, 0
Deck Dist Width WeirC Skew NumUp NumDn MinLoCord MaxHiCord MaxSubmerge Is_Ogee
26.588450,50.000000,2.6,0, 57, 57, , , 0.95, 0, 0,0,,
 9731.33 9740.95 9751.34 9761.72 9762.28 9772.10 9782.48 9792.86 9799.53 9803.24
 9813.62 9824.00 9834.38 9836.79 9844.76 9855.15 9865.53 9874.04 9875.91 9886.29
 9896.67 9907.05 9911.30 9917.43 9917.81 9958.21 9958.2110050.2110050.2110054.00
10060.3210062.7610073.1510083.5310093.9110097.5710104.2910114.6710125.0510134.82
10135.4310145.8110156.1910166.5710172.0810176.9610187.3410197.7210208.1010209.33
10218.4810228.8610239.2410246.5910249.6210260.0010268.12
   73.14   73.36   73.75   73.75   73.78   74.37   74.39   74.46   74.46   74.45
   74.67   74.62   74.69   74.70   74.69   74.63   74.59   74.54   74.53   74.57
   74.50   74.52   74.46   74.37   74.33   74.58   74.58   75.16   75.16   75.19
   75.23   75.25   75.30   75.23   75.35   75.33   75.28   75.35   75.47   75.47
   75.46   75.62   75.50   75.60   75.58   75.55   75.56   75.58   75.54   75.56
   75.65   75.71   75.91   76.00   76.02   76.15   76.28
 -926.86 -926.64 -926.25 -926.25 -926.22 -925.63 -925.61 -925.54 -925.54 -925.55
 -925.33 -925.38 -925.31 -925.30 -925.31 -925.37 -925.41 -925.46 -925.47 -925.43
 -925.50 -925.48 -925.54 -925.63 -925.67 -925.42   68.58   69.16 -924.84 -924.81
 -924.77 -924.75 -924.70 -924.77 -924.65 -924.67 -924.72 -924.65 -924.53 -924.53
 -924.54 -924.38 -924.50 -924.40 -924.42 -924.45 -924.44 -924.42 -924.46 -924.44
 -924.35 -924.29 -924.09 -924.00 -923.98 -923.85 -923.72
 9731.33 9740.95 9751.34 9761.72 9762.28 9772.10 9782.48 9792.86 9799.53 9803.24
 9813.62 9824.00 9834.38 9836.79 9844.76 9855.15 9865.53 9874.04 9875.91 9886.29
 9896.67 9907.05 9911.30 9917.43 9917.81 9944.69 9944.6910036.6910036.6910054.00
10060.3210062.7610073.1510083.5310093.9110097.5710104.2910114.6710125.0510134.82
10135.4310145.8110156.1910166.5710172.0810176.9610187.3410197.7210208.1010209.33
10218.4810228.8610239.2410246.5910249.6210260.0010268.12
   73.14   73.36   73.75   73.75   73.78   74.37   74.39   74.46   74.46   74.45
   74.67   74.62   74.69   74.70   74.69   74.63   74.59   74.54   74.53   74.57
   74.50   74.52   74.46   74.37   74.33   74.50   74.50   75.08   75.08   75.19
   75.23   75.25   75.30   75.23   75.35   75.33   75.28   75.35   75.47   75.47
   75.46   75.62   75.50   75.60   75.58   75.55   75.56   75.58   75.54   75.56
   75.65   75.71   75.91   76.00   76.02   76.15   76.28
 -926.86 -926.64 -926.25 -926.25 -926.22 -925.63 -925.61 -925.54 -925.54 -925.55
 -925.33 -925.38 -925.31 -925.30 -925.31 -925.37 -925.41 -925.46 -925.47 -925.43
 -925.50 -925.48 -925.54 -925.63 -925.67 -925.50   68.50   69.08 -924.92 -924.81
 -924.77 -924.75 -924.70 -924.77 -924.65 -924.67 -924.72 -924.65 -924.53 -924.53
 -924.54 -924.38 -924.50 -924.40 -924.42 -924.45 -924.44 -924.42 -924.46 -924.44
 -924.35 -924.29 -924.09 -924.00 -923.98 -923.85 -923.72
BR Coef=-1 , 0 , 0 ,, 0 ,,,0.8,0,1,0,
WSPro=,,,, 1 ,,,, 0 ,,,, 0 ,,,,-1 ,-1 ,-1 , 0 , 0 , 0 , 0 , 0
BC Design=,, 0 ,, 0 ,,,,,,

Type RM Length L Ch R = 1 , 5373.45,474.249100,474.249100,474.249100
XS GIS Cut Line= 3
864847.848077714767164.504337576864918.620191098767181.755774164
 865420.44252382767337.192295387
#Sta/Elev= 30
9755.44874.233819824.56674.684349839.25775.030559876.84674.952079918.72175.28644
 9929.1974.876169939.65873.895729950.12769.793129960.59664.530519971.06562.77987
9992.00253.4166210002.4753.4318910012.9456.6125510023.4165.6475510033.8872.09193
10042.0573.3662910054.8173.4096210065.2875.1925810086.22 74.280310149.0374.75088
10169.9775.3603710190.9175.5731110211.8575.3633510243.2576.1011110253.7275.87255
10264.1976.3812710274.6676.24673 10295.676.5640510316.5376.0387710353.64 76.2566
#Mann= 3 , 0 , 0
9755.448    0.06       09755.448    0.06       010353.64    0.06       0
#XS Ineff= 2 , 0
       0                               0
Bank Sta=9755.448,10353.64
Exp/Cntr=0.3,0.1

Type RM Length L Ch R = 1 ,4899.201,459.739600,459.739600,459.739600
XS GIS Cut Line= 4
864230.458102916767239.053286121864808.980777868767462.312789582
 864963.49264103767526.385030588 865232.36470491 767640.50415178
#Sta/Elev= 30
9329.50676.631939452.28174.951489495.15672.463989623.78273.709989859.59672.90471
9870.31568.826389881.03462.551899891.75260.348869923.90961.261069945.34668.83103
 9956.1368.064299988.60753.595229999.43251.3949710031.9156.3247110053.5663.06713
10064.3962.8863410075.2166.4981110086.0466.2952410096.8668.4896610107.6973.02918
10118.5274.6116310129.3870.9383310140.2564.8507910151.1161.5680710205.4364.46939
10238.0273.2605410248.8874.5372210292.3473.6111310324.9375.2054410408.9775.63923
#Mann= 3 , 0 , 0
9329.506  0.0656       09329.506  0.0656       010408.97  0.0656       0
#XS Ineff= 2 , 0
       09952.388                       0
Bank Sta=9329.506,10408.97
Exp/Cntr=0.3,0.1

Type RM Length L Ch R = 1 ,4439.461,0.000000,0.000000,0.000000
XS GIS Cut Line= 3
864350.738293399768824.646627315864642.470583954767953.470738519
865206.770298598767754.568760914
#Sta/Elev= 30
8829.901 78.96718882.25778.834088903.34977.434098987.71579.128739082.62778.96158
9103.71977.343649135.35677.480579156.44879.745669188.08580.069389230.26877.97731
9282.99777.880729304.08975.986549335.72675.923859504.65578.678789641.55575.08629
9704.82976.346569793.71970.788029846.734 70.3746 9867.9472.404739878.543  71.308
9910.35361.189849952.76558.226349984.574 49.668710037.5950.9706910058.7953.55048
10111.81  71.73810133.0275.6557110207.24 75.050510249.6576.5195610346.9576.65203
#Mann= 3 , 0 , 0
8829.901    0.04       08829.901    0.04       010346.95    0.04       0
#XS Ineff= 2 , 0
       09871.535                       0
Bank Sta=8829.901,10346.95
Exp/Cntr=0.3,0.1